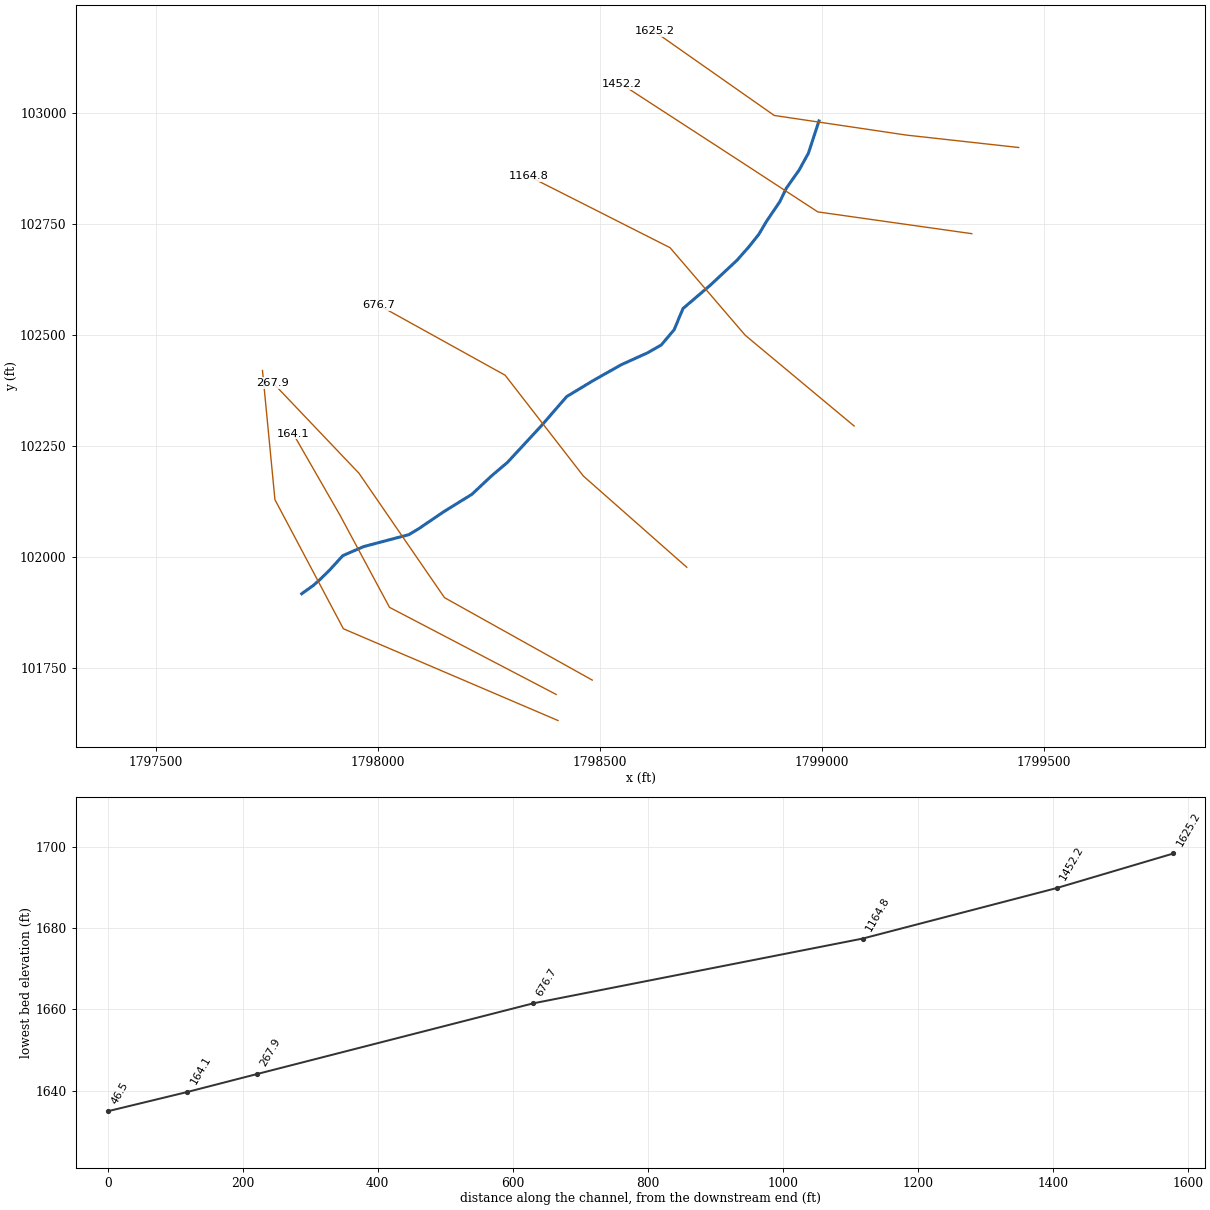
--- Duskins Branch.prj (project) ---

Proj Title=Duskins Branch
Current Plan=p01
Default Exp/Contr=0,0
English Units
Geom File=g01
Flow File=f01
Plan File=p01
BEGIN DESCRIPTION:
END DESCRIPTION:
DSS Export Rating Curves= 0
DSS Export Rating Curve Sorted= 0
DSS Export Volume Flow Curves= 0
DXF OffsetX= 0
DXF OffsetY= 0
DXF ScaleX= 0
DXF ScaleY= 0

--- Duskins Branch.p01 (plan) ---

Plan Title=Floodplain
Program Version=4.00
Geom File=g01
Flow File=f01
K Sum by GR=0
Std Step Tol=0.01
Critical Tol=0.01
Num of Std Step Trials=20
Max Error Tol=0.3
Flow Tol Ratio=0.001
Split Flow NTrial=30
Split Flow Tol=0.02
Split Flow Ratio=0.02
Log Output Level=0
Friction Slope Method=1
Unsteady Friction Slope Method=2
Unsteady Bridges Friction Slope Method=1
Global Log Level=0
CheckData=False
Run HTab=0
Run UNet=0
Run PostProcess=0
UNET Theta=0
UNET Theta Warmup=0
UNET ZTol=0
UNET ZSATol=0
UNET MxIter=0
UNET MaxInSteps=0
UNET DtIC=0
UNET DtMin=0
UNET MaxCRTS=0
UNET WFStab=0
UNET SFStab=0
UNET WFX=0
UNET SFX=0
UNET DSS MLevel=0
UNET DZMax Abort=0
UNET Convert EG Bridges=0
UNET Use Existing IB Tables=0
UNET Froude Limit=0
UNET Froude Power=0
Write IC File=0
Echo Input=False
Echo Output=False
Write Detailed=0

--- Duskins Branch.f01 (steady flow) ---

Flow Title=NFF Regression Equation
Program Version=4.00
Number of Profiles=1
Profile Names=P100yr
River Rch & RM=Duskins Branch,Main      ,1625.2
500.3972
River Rch & RM=Duskins Branch,Main      ,1452.2
563.8125
River Rch & RM=Duskins Branch,Main      ,267.9
590.5297
Boundary for River Rch & Prof#=Duskins Branch,Main      ,1
Up Type=0
Dn Type=3
Dn Slope=0.038722

--- Duskins Branch.g01 (geometry) ---

Geom Title=USGS 10m DEM
Program Version=4.00

River Reach=Duskins Branch  ,Main
Reach XY= 30
     1798993.303      102982.028     1798969.512      102909.298
     1798948.494      102871.202      1798919.88      102830.708
     1798905.143      102800.265      1798874.93      102755.601
     1798857.852      102726.701       1798835.9        102699.1
     1798809.247      102668.901      1798748.82      102612.414
     1798687.421      102559.957      1798667.18      102511.881
      1798638.27      102477.713     1798607.568      102460.142
     1798548.302      102433.316     1798485.294      102397.757
     1798425.404      102361.574      1798368.01      102295.446
     1798292.034      102213.362      1798256.01       102182.88
     1798212.282      102141.745      1798148.86      102102.518
     1798092.971      102064.544     1798070.038      102050.784
     1797968.739      102024.004      1797921.63      102003.682
     1797892.072      101971.353     1797869.789      101949.444
     1797854.349      101935.875     1797829.135      101917.848

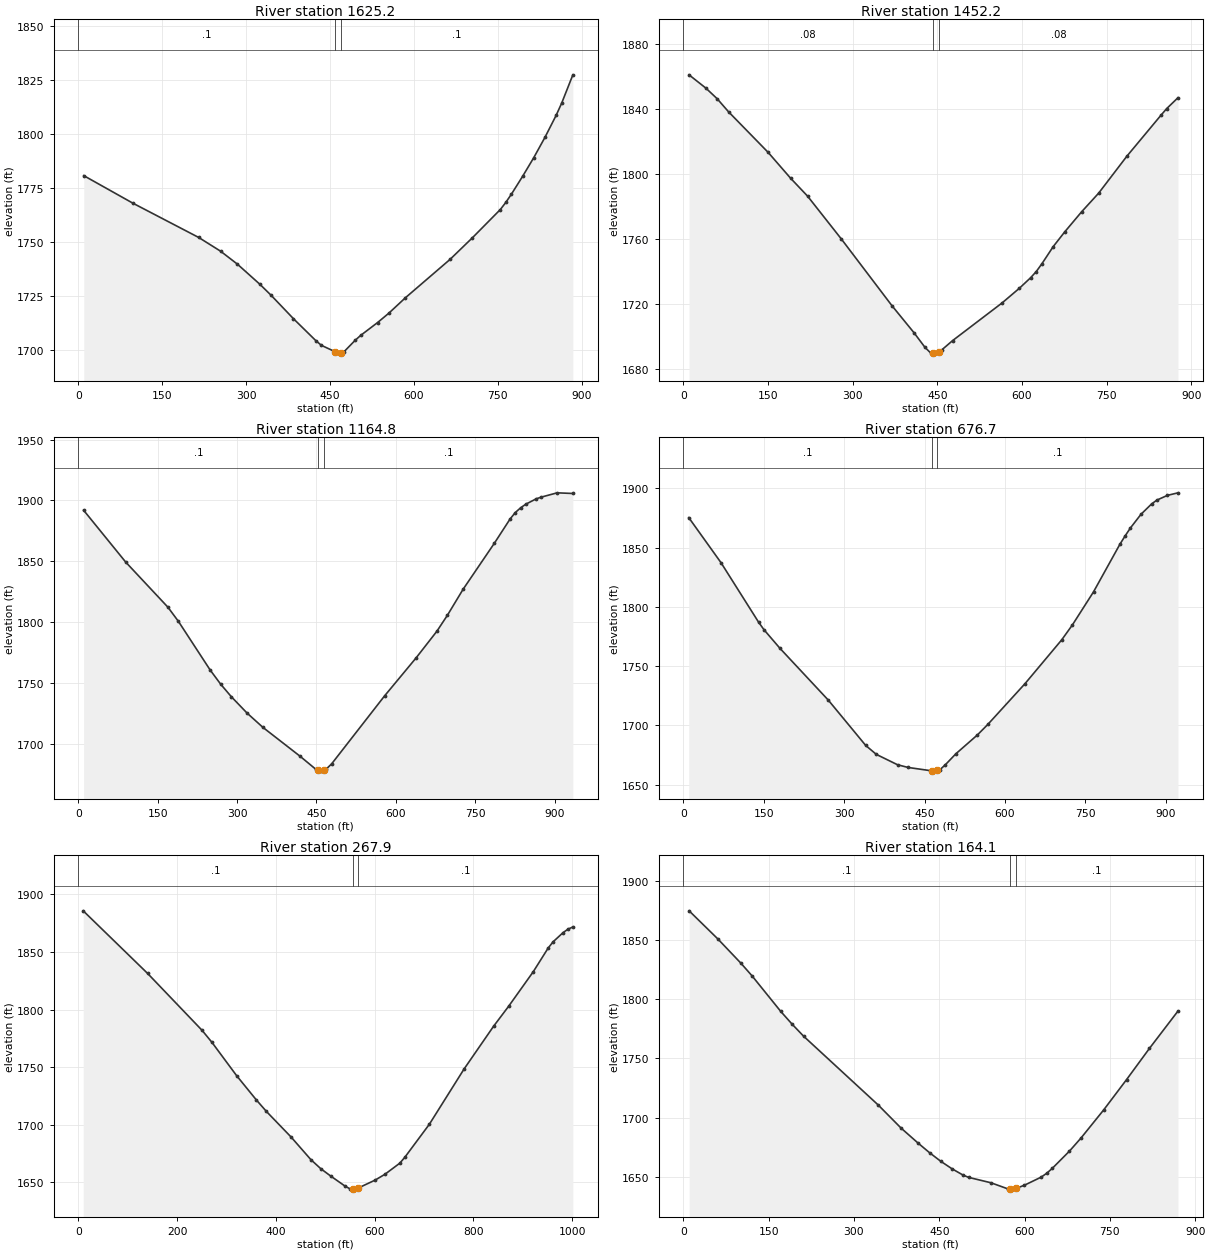
Type RM Length L Ch R = 1 ,1625.2  ,181.7,173.1,164.4
XS GIS Cut Line= 4
     1799442.935      102922.238     1799190.011      102950.211
     1798892.642      102994.384     1798623.045      103183.452
#Sta/Elev= 30
     9.8 1780.59    97.9 1767.79   215.3 1751.95   254.5 1745.58   284.5 1739.59
   324.6 1730.29   344.7 1725.19   384.7 1714.33   424.8 1704.14   434.8 1701.96
   459.9 1698.94   464.9 1698.36   469.9 1698.64   474.9 1698.93     495 1704.27
     505 1706.58   535.1  1712.5   555.1 1716.81     585 1724.02   664.9 1741.81
   704.8 1751.81   754.7 1764.89   764.6 1768.22   774.6 1772.04   794.6 1780.29
   814.5 1788.92   834.5 1798.33   854.4 1808.47   864.4 1814.17   884.4 1827.29
#Mann= 3 , 0 , 0
       0      .1       0   459.9    .045       0   469.9      .1       0
Bank Sta=459.9,469.9
XS Rating Curve= 0 ,0
Exp/Cntr=0.3,0.1

Type RM Length L Ch R = 1 ,1452.2  ,293.1,287.4,281.8
XS GIS Cut Line= 4
     1799337.303      102728.288     1798990.678      102777.306
     1798819.116      102889.346     1798549.519      103064.409
#Sta/Elev= 30
      10 1861.06      40 1852.84      60  1846.3      80 1838.32     150 1813.42
     190 1797.44     220 1786.45   280.1 1759.97   369.6 1719.01   408.6 1702.41
   428.1 1693.39   437.9 1690.03   442.6 1689.94   447.6 1689.84   452.6 1690.79
   457.4 1691.69   476.9 1697.51     565  1720.8   595.2  1729.7   615.3 1736.23
   625.3 1740.04   635.3 1744.84   655.4 1755.42   675.5 1764.34   705.7 1776.81
   735.8 1788.24     786 1811.07   846.3 1836.22   856.3 1840.25   876.4 1846.98
#Mann= 3 , 0 , 0
       0     .08       0   442.6    .045       0   452.6     .08       0
Bank Sta=442.6,452.6
XS Rating Curve= 0 ,0
Exp/Cntr=0.3,0.1

Type RM Length L Ch R = 1 ,1164.8  ,489,488,487.1
XS GIS Cut Line= 4
     1799072.393      102295.413     1798827.451      102499.505
     1798658.058      102696.777     1798340.726      102857.324
#Sta/Elev= 30
      10 1891.93    89.7 1849.22   169.4 1812.16   189.3 1800.48   249.1  1760.6
     269 1748.92   288.9 1738.72   318.8 1725.19   348.8  1713.4   418.8 1689.74
   448.8 1678.94   453.8 1678.17   458.8 1677.41   463.8 1678.31   468.8 1679.21
   478.8 1683.43   578.8 1739.29   638.1  1770.4   677.6 1792.43   697.4 1805.51
     727 1826.85   786.3 1864.84   815.9 1884.71   825.8 1890.02   835.7 1893.86
   845.6 1896.87   865.3 1901.28   875.2 1902.72   904.8  1906.2   934.5 1905.66
#Mann= 3 , 0 , 0
       0      .1       0   453.8    .045       0   463.8      .1       0
Bank Sta=453.8,463.8
XS Rating Curve= 0 ,0
Exp/Cntr=0.3,0.1

Type RM Length L Ch R = 1 ,676.7   ,409.8,408.9,408
XS GIS Cut Line= 4
     1798695.705      101977.416      1798462.97      102182.738
     1798286.924      102409.673     1798002.528      102567.222
#Sta/Elev= 30
      10 1875.26    70.1  1837.3   140.2 1787.14   150.2  1780.8   180.2    1765
   270.3 1721.37   340.1 1683.15   359.9  1675.6   399.5 1666.85   419.3 1664.56
   463.8 1661.68   468.8 1661.47   473.8  1662.1   478.7 1662.71   488.6 1666.78
   508.4 1676.12   548.1 1691.81   567.9 1700.82     637 1735.06   705.9 1772.23
   725.7 1784.73   765.1 1812.61   814.3 1852.73   824.2 1859.89     834 1866.53
   853.7 1878.04   873.4 1886.74   883.3    1890     903 1893.99   922.7 1896.14
#Mann= 3 , 0 , 0
       0      .1       0   463.8    .045       0   473.8      .1       0
Bank Sta=463.8,473.8
XS Rating Curve= 0 ,0
Exp/Cntr=0.3,0.1

Type RM Length L Ch R = 1 ,267.9   ,106.1,103.8,101.3
XS GIS Cut Line= 4
     1798482.995      101723.426     1798150.375      101908.993
     1797957.806      102189.094     1797764.377      102392.299
#Sta/Elev= 30
      10 1885.72   140.3  1831.4   250.6 1781.97   270.6 1771.53   320.7 1742.53
   360.8 1721.38   380.9 1711.53   430.9 1689.29   470.9 1669.69   490.9 1661.85
   510.8 1655.51   540.8 1646.49   550.8  1644.2   555.8 1644.14   560.8 1644.08
   565.8 1644.83   600.8 1651.88   620.8 1656.96   650.8 1666.57   660.8 1671.55
   710.8 1700.43   780.9 1748.29     841 1785.62   871.1 1802.75   921.2  1832.9
   951.2 1853.35   961.3 1858.83   981.3 1866.73   991.3 1869.77  1001.3 1871.69
#Mann= 3 , 0 , 0
       0      .1       0   555.8    .045       0   565.8      .1       0
Bank Sta=555.8,565.8
XS Rating Curve= 0 ,0
Exp/Cntr=0.3,0.1

Type RM Length L Ch R = 1 ,164.1   ,117.7,117.6,117.5
XS GIS Cut Line= 4
     1798401.661      101691.203     1798026.682      101887.126
     1797915.096      102094.727     1797809.998      102277.676
#Sta/Elev= 30
    10.1 1874.58    60.4 1850.95   100.7 1830.61   120.9  1819.6   171.2 1789.68
   191.4 1778.79   211.5  1768.7   342.5 1710.72   382.8 1691.19     413  1678.4
   432.9  1670.4   452.5 1663.19   472.2 1656.88   491.8  1651.5   501.6 1649.56
   540.9 1645.01   570.4  1639.9   575.2 1639.77   580.2 1639.64   585.2 1640.27
   599.8 1642.96   629.3 1649.79   639.1 1653.08   648.9 1657.25   678.9  1671.7
     699 1682.64   739.1 1706.49   779.3 1732.05   819.5 1758.37   869.8 1789.96
#Mann= 3 , 0 , 0
       0      .1       0   575.2    .045       0   585.2      .1       0
Bank Sta=575.2,585.2
XS Rating Curve= 0 ,0
Exp/Cntr=0.3,0.1

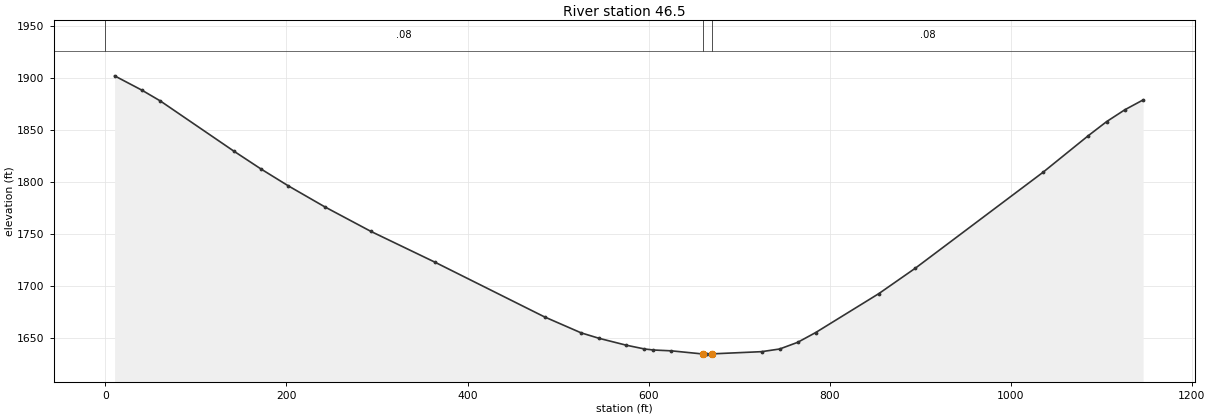
Type RM Length L Ch R = 1 ,46.5    ,43.7,46.5,49.3
XS GIS Cut Line= 4
     1798405.967      101632.393     1797922.793      101838.968
     1797768.737      102129.573     1797740.727      102420.177
#Sta/Elev= 30
    10.1 1901.92    40.4 1888.11    60.6 1877.84   141.5 1829.88   171.8 1812.57
   202.1 1796.32   242.5 1776.13   293.1 1752.74   363.8 1723.21   485.1 1670.61
   525.5 1655.32   545.4 1650.06   575.3 1643.49   595.3 1639.89   605.2 1638.87
   625.2 1638.07     660 1635.04     665 1634.91     670 1635.16   724.8 1637.27
   744.8 1639.83   764.7 1646.23   784.6 1655.62   854.4 1692.99   894.7 1717.37
  1035.6 1809.29  1085.9  1844.6  1106.1 1858.06  1126.2  1869.4  1146.3 1878.81
#Mann= 3 , 0 , 0
       0     .08       0     660    .045       0     670     .08       0
Bank Sta=660,670
XS Rating Curve= 0 ,0
Exp/Cntr=0.3,0.1

Chan Stop Cuts=-1
Use User Specified Reach Order=0